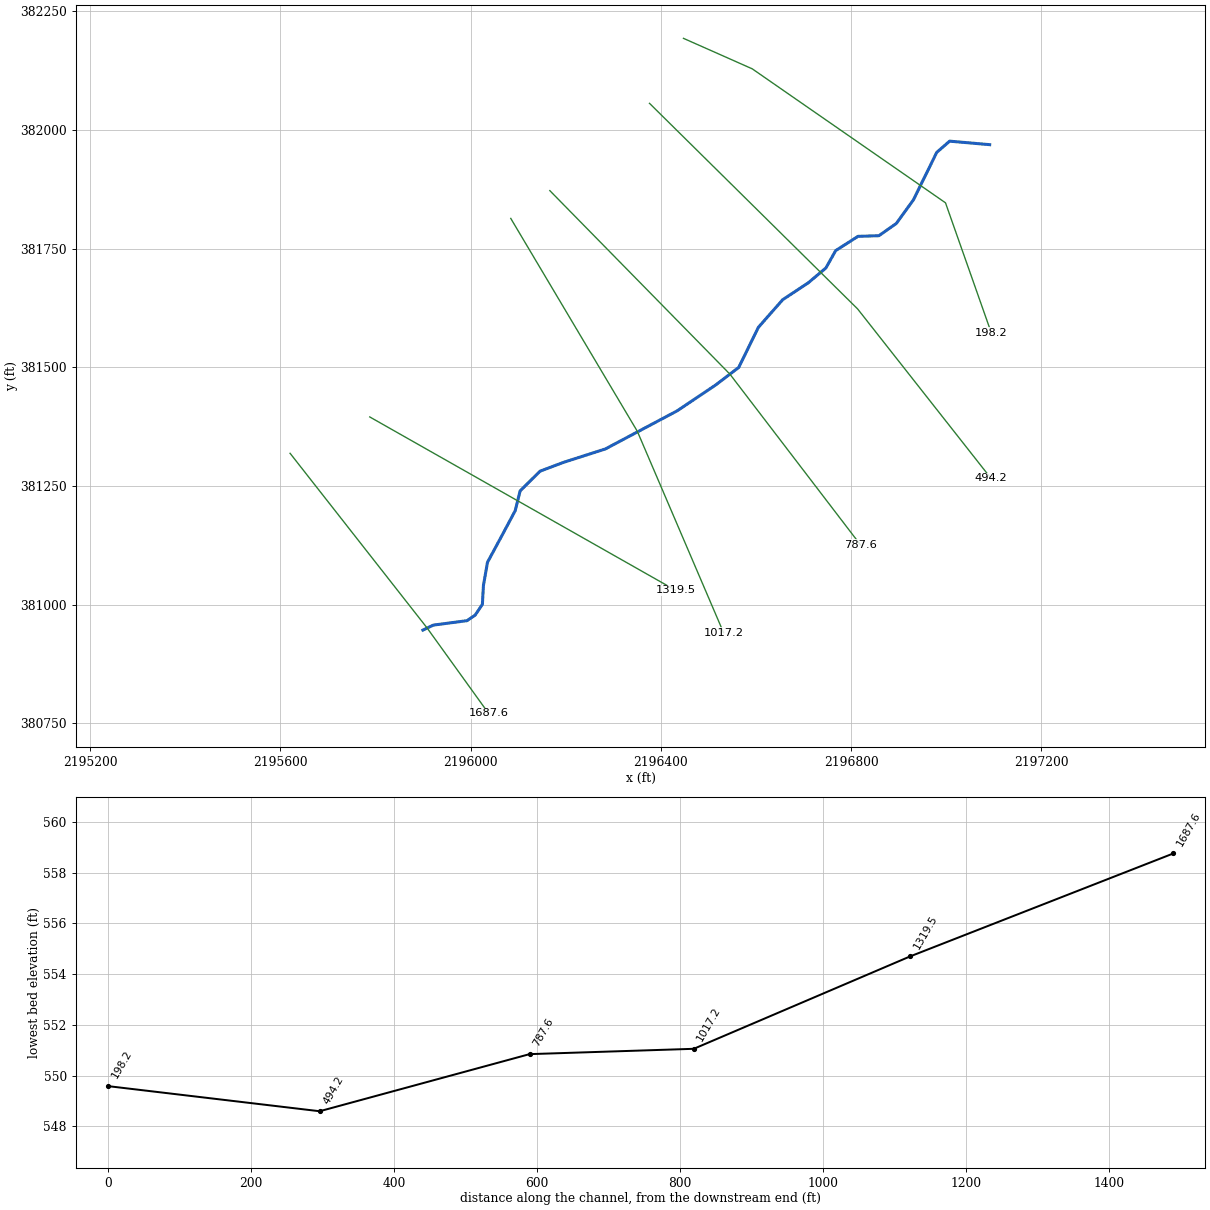
--- DANSRUN.prj (project) ---

Proj Title=DANSRUN
Current Plan=p01
Default Exp/Contr=0,0
English Units
Geom File=g01
Flow File=f01
Plan File=p01
BEGIN DESCRIPTION:
END DESCRIPTION:
DSS Export Rating Curves= 0
DSS Export Rating Curve Sorted= 0
DSS Export Volume Flow Curves= 0
DXF OffsetX= 0
DXF OffsetY= 0
DXF ScaleX= 0
DXF ScaleY= 0

--- DANSRUN.p01 (plan) ---

Plan Title=Floodplain
Program Version=4.00
Geom File=g01
Flow File=f01
K Sum by GR=0
Std Step Tol=0.01
Critical Tol=0.01
Num of Std Step Trials=20
Max Error Tol=0.3
Flow Tol Ratio=0.001
Split Flow NTrial=30
Split Flow Tol=0.02
Split Flow Ratio=0.02
Log Output Level=0
Friction Slope Method=1
Unsteady Friction Slope Method=2
Unsteady Bridges Friction Slope Method=1
Global Log Level=0
CheckData=False
Run HTab=0
Run UNet=0
Run PostProcess=0
UNET Theta=0
UNET Theta Warmup=0
UNET ZTol=0
UNET ZSATol=0
UNET MxIter=0
UNET MaxInSteps=0
UNET DtIC=0
UNET DtMin=0
UNET MaxCRTS=0
UNET WFStab=0
UNET SFStab=0
UNET WFX=0
UNET SFX=0
UNET DSS MLevel=0
UNET DZMax Abort=0
UNET Convert EG Bridges=0
UNET Use Existing IB Tables=0
UNET Froude Limit=0
UNET Froude Power=0
Write IC File=0
Echo Input=False
Echo Output=False
Write Detailed=0

--- DANSRUN.f01 (steady flow) ---

Flow Title=NFF Regression Equation
Program Version=4.00
Number of Profiles= 1
Profile Names=P100yr
River Rch & RM=DANSRUN,Main            ,1687.6
     921
River Rch & RM=DANSRUN,Main            ,198.2
     950
Boundary for River Rch & Prof#=DANSRUN,Main            , 1
Up Type= 0
Dn Type= 3
Dn Slope=4.179728E-03
DSS Import GetInterval= 0
DSS Import GetPeak= 0
DSS Import FillOption= 0

--- DANSRUN.g01 (geometry) ---

Geom Title=USGS 10m DEM
Program Version=4.00

River Reach=DANSRUN     ,Main
Reach XY= 30
     2195899.495      380946.516     2195921.526      380957.033
     2195992.357      380966.401     2196009.414      380978.034
     2196010.114      380979.079     2196024.623      381000.642
     2196026.909      381040.963     2196035.362      381089.279
     2196066.332      381146.772     2196093.669      381198.127
     2196103.933      381239.680     2196145.918      381281.336
     2196194.730      381299.788     2196271.663      381324.477
     2196283.212      381328.184     2196434.433      381408.620
     2196515.493      381463.206     2196563.667      381499.972
     2196604.934      381584.426     2196656.036      381642.590
     2196709.704      381678.124     2196746.864      381709.417
     2196767.523      381746.118     2196814.481      381776.156
     2196858.434      381777.530     2196894.982      381803.261
     2196930.890      381852.862     2196980.049      381953.142
     2197007.162      381976.713     2197091.383      381969.329

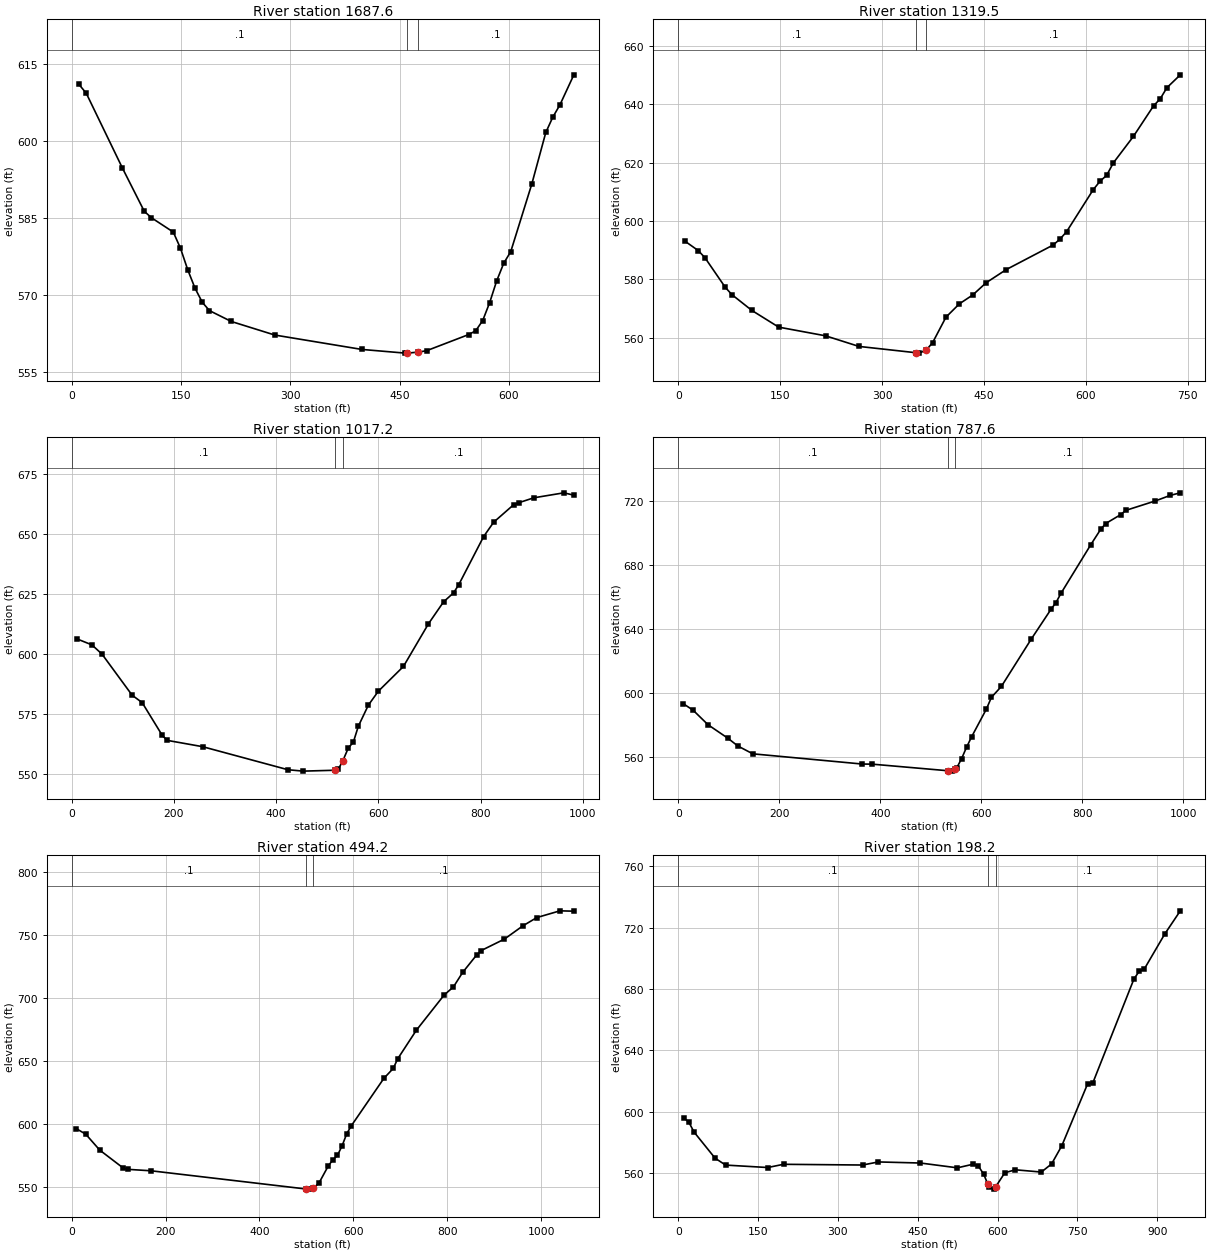
Type RM Length L Ch R = 1 ,1687.6,365.2,368.2,378.2
XS GIS Cut Line= 3
     2195620.267      381319.070     2195908.519      380950.824
     2196037.682      380771.050
#Sta/Elev= 30
     9.9  611.05    19.9  609.33    69.6  594.75    99.5  586.36   109.4  585.10
   139.3  582.32   149.2  579.16   159.2  574.96   169.1  571.41   179.1  568.65
   189.0  567.03   218.9  564.92   278.6  562.28   398.0  559.48   457.7  558.76
   460.1  558.76   475.1  558.95   486.9  559.23   544.6  562.37   554.3  563.11
   563.9  565.09   573.5  568.60   583.1  572.82   592.8  576.26   602.4  578.51
   631.3  591.67   650.5  601.70   660.1  604.68   669.8  607.05   689.0  612.92
#Mann= 3 , 0 , 0
       0     0.1       0   460.1   0.045       0   475.1     0.1       0
Bank Sta=   460.1,   475.1
Exp/Cntr=0.3,0.1

Type RM Length L Ch R = 1 ,1319.5,314.4,302.3,287.4
XS GIS Cut Line= 2
     2195787.796      381395.659     2196430.359      381030.653
#Sta/Elev= 30
     9.9  593.10    29.6  589.85    39.4  587.40    69.0  577.35    78.8  574.80
   108.4  569.34   147.8  563.62   216.8  560.64   266.0  557.00   350.2  554.83
   354.7  554.70   365.2  555.78   374.4  558.29   394.1  567.05   413.8  571.61
   433.5  574.65   453.3  578.86   482.8  583.36   551.8  591.78   561.6  593.74
   571.5  596.31   610.9  610.79   620.8  613.65   630.6  615.69   640.5  619.98
   670.0  629.05   699.6  639.51   709.4  641.93   719.3  645.75   739.0  650.16
#Mann= 3 , 0 , 0
       0     0.1       0   350.2   0.045       0   365.2     0.1       0
Bank Sta=   350.2,   365.2
Exp/Cntr=0.3,0.1

Type RM Length L Ch R = 1 ,1017.2,224,229.5,235.1
XS GIS Cut Line= 3
     2196084.364      381813.895     2196350.514      381365.242
     2196531.699      380941.249
#Sta/Elev= 30
     9.8  606.32    39.4  603.79    59.1  599.95   118.1  582.78   137.8  579.67
   177.2  565.96   187.0  563.90   255.9  561.28   423.2  551.64   452.8  551.06
   515.3  551.43   521.7  551.86   530.3  555.27   541.3  560.74   551.1  563.16
   560.9  569.81   580.5  578.62   600.1  584.45   649.2  594.79   698.2  612.62
   727.7  621.76   747.3  625.52   757.1  628.79   806.2  649.05   825.8  655.03
   865.0  662.35   874.8  663.15   904.3  665.21   963.1  667.29   982.7  666.31
#Mann= 3 , 0 , 0
       0     0.1       0   515.3   0.045       0   530.3     0.1       0
Bank Sta=   515.3,   530.3
Exp/Cntr=0.3,0.1

Type RM Length L Ch R = 1 ,787.6,292.9,293.4,296.6
XS GIS Cut Line= 3
     2196166.467      381872.472     2196545.116      381485.814
     2196819.711      381126.016
#Sta/Elev= 30
     9.8  593.09    29.5  588.96    59.0  579.88    98.4  571.41   118.1  566.56
   147.6  561.68   364.1  555.29   383.7  555.22   533.7  551.09   541.2  550.85
   548.7  552.28   551.0  552.72   560.9  558.69   570.7  565.80   580.5  572.20
   610.1  589.79   619.9  597.03   639.6  603.86   698.6  633.42   738.0  652.21
   747.8  656.39   757.6  662.15   816.7  692.62   836.4  702.30   846.2  705.84
   875.7  711.37   885.6  714.02   944.6  719.99   974.1  723.47   993.8  725.04
#Mann= 3 , 0 , 0
       0     0.1       0   533.7   0.045       0   548.7     0.1       0
Bank Sta=   533.7,   548.7
Exp/Cntr=0.3,0.1

Type RM Length L Ch R = 1 ,494.2,292.2,296,299.9
XS GIS Cut Line= 3
     2196376.060      382056.401     2196813.687      381623.183
     2197094.144      381266.129
#Sta/Elev= 30
     9.9  596.47    29.8  592.15    59.6  579.53   109.3  565.42   119.2  564.28
   168.8  563.14   498.8  548.72   506.5  548.60   513.8  549.21   526.4  553.21
   546.3  566.81   556.2  571.83   566.1  575.35   576.1  583.05   586.0  592.60
   595.9  598.95   665.1  636.45   684.9  644.24   694.7  652.02   734.2  674.53
   793.5  702.49   813.2  708.86   832.9  720.38   862.5  734.12   872.4  737.70
   921.8  746.77   961.2  757.29   990.9  763.85  1040.2  769.19  1069.8  768.91
#Mann= 3 , 0 , 0
       0     0.1       0   498.8   0.045       0   513.8     0.1       0
Bank Sta=   498.8,   513.8
Exp/Cntr=0.3,0.1

Type RM Length L Ch R = 1 ,198.2,223,198.2,173.4
XS GIS Cut Line= 4
     2196447.459      382193.372     2196592.069      382129.117
     2196998.424      381846.808     2197094.666      381573.053
#Sta/Elev= 30
     9.9  596.18    19.8  593.30    29.7  586.79    69.2  569.77    89.0  565.26
   168.1  563.67   197.8  565.77   346.3  565.30   376.0  567.31   455.1  566.60
   524.4  563.47   554.1  565.84   564.0  564.55   573.9  559.27   581.5  552.87
   583.8  550.93   593.7  549.59   596.5  551.19   613.5  560.25   633.2  562.20
   682.1  560.71   701.4  566.01   720.7  577.94   769.1  618.26   778.8  618.78
   856.2  686.64   865.8  691.46   875.5  693.01   914.2  715.99   943.2  730.97
#Mann= 3 , 0 , 0
       0     0.1       0   581.5   0.045       0   596.5     0.1       0
Bank Sta=   581.5,   596.5
Exp/Cntr=0.3,0.1